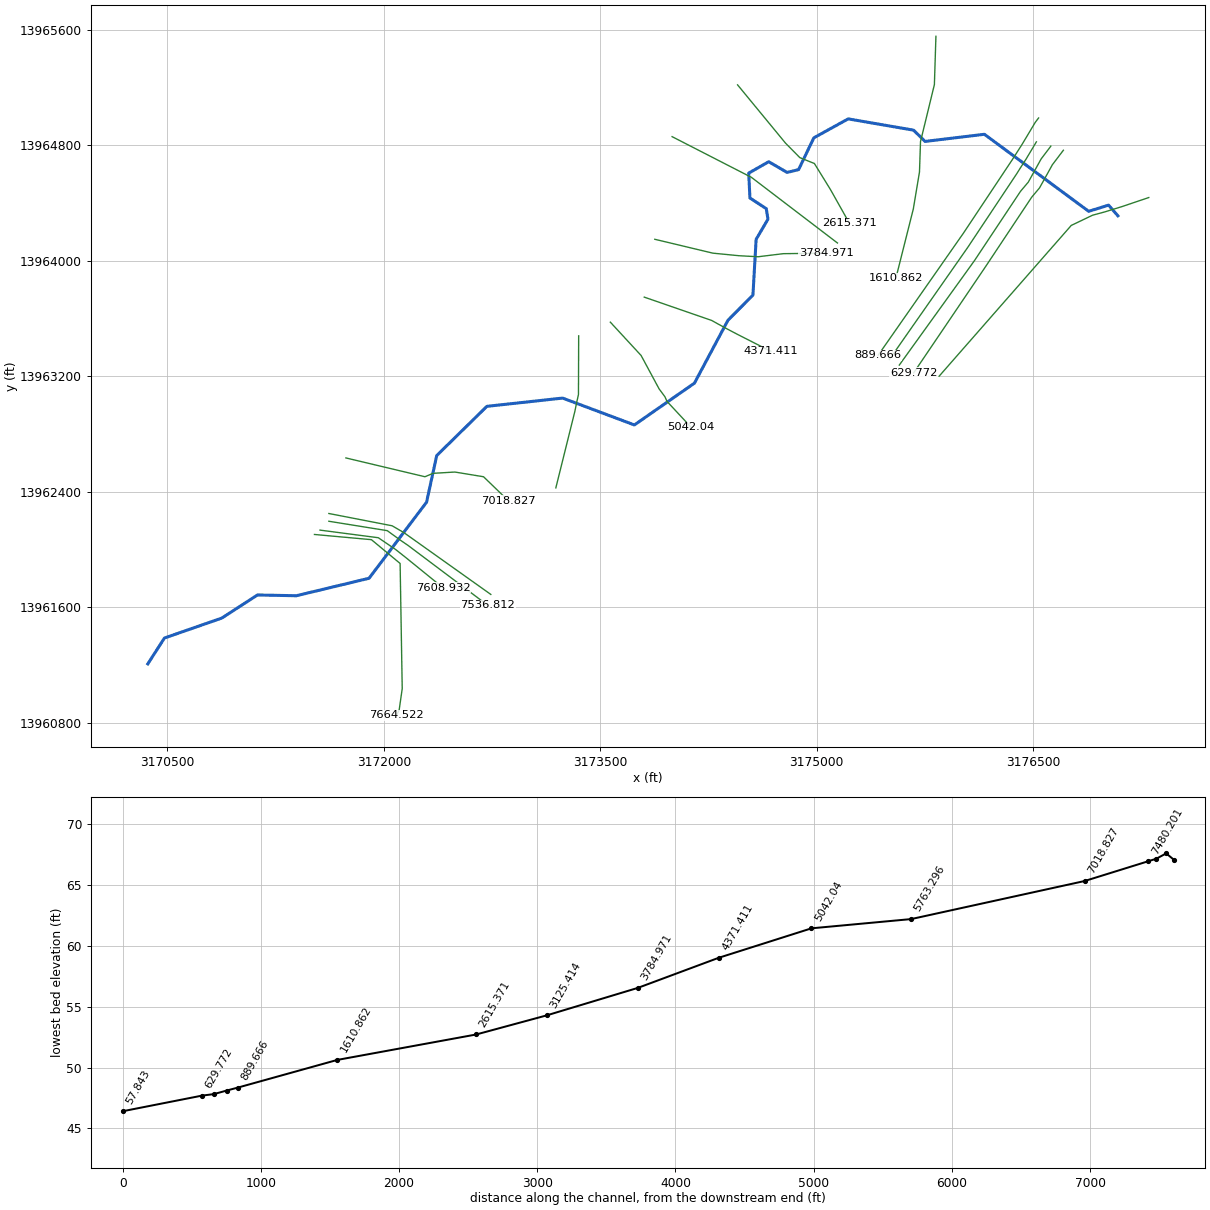
--- G103-80-031A.prj (project) ---

Proj Title=G103-80-03.1a
Current Plan=p02
Default Exp/Contr=.3,.1
English Units
Geom File=g01
Flow File=f01
Flow File=f02
Plan File=p01
Plan File=p02
Y Axis Title=Elevation
X Axis Title(PF)=Main Channel Distance
X Axis Title(XS)=Station
BEGIN DESCRIPTION:
HCFCD MODEL SUMMARY METADATA
The purpose of this summary is to document the high points of hydrologic and hydraulic models filed within the HCFCD Model and Map Management (M3) system.  The document includes references to the project that prompted the creation or update of the model.
DESCRIPTION OF PROJECT:
The following model was the hydraulic model which represented the effective condition of Harris County's watersheds.
PURPOSE OF PROJECT:
Development of effective models to support the National Flood Insurance Program.
HCFCD Watershed Unit ID: G
M3 Study Identifier: 2007_Effective_G
Engineer: HCFCD
Project Name: EffectiveFEMA Study for watershed San Jancinto River (G)
Study Completion Date: 6/18/2007
FEMA Case Number: [No Data]
FEMA Approval Date: [No Date in Database]
Vertical Datum: NAVD 1988
Datum Note: 2001 ADJ
HYDRAULICS
HCFCD Unit No.:  G103-80-03
Hydraulic Program Name: HEC-RAS
Hydraulic Program Version: 3.0.1
Steady Hydraulic Model: Yes
Unsteady Hydraulic Model: No
Update 1: The effective FEMA hydraulic model for unit number G103-80-031A has been updated by FEMA LOMR 16-06-1829P with an effective date of 2/24/2017.
END DESCRIPTION:
DSS Export Rating Curves= 0
DSS Export Rating Curve Sorted= 0
DSS Export Volume Flow Curves= 0
DXF OffsetX= 0
DXF OffsetY= 0
DXF ScaleX= 1
DXF ScaleY= 10

--- G103-80-031A.p02 (plan) ---

Plan Title=FEMA Effective Floodway 2016
Version=Version 3.0.1  May 2012
Short Identifier=Eff+LOMR_FW
Geom File=g01
Flow File=f02
Subcritical Flow
K Sum by GR= 0
Std Step Tol= 0.01
Critical Tol= 0.01
Num of Std Step Trials= 20
Max Error Tol= 0.3
Flow Tol Ratio= 0.001
Split Flow NTrial= 30
Split Flow Tol= 0.02
Split Flow Ratio= 0.02
Log Output Level= 0
Friction Slope Method= 1
Unsteady Friction Slope Method= 2
Parabolic Critical Depth
Global Vel Dist= 0 , 0 , 0
Global Log Level= 0
CheckData=True
Encroach Param=-1 ,0,0, 2
Encroach River=G103-80-031A
Encroach Reach=G10380031A_0001
Encroach Node=8841.547
       1     400  446.82
Encroach Node=7664.522
       1     543  589.32
Encroach Node=7608.932
       1  517.31  565.86
Encroach Node=7572.872
       1  517.31  565.86
Encroach Node=7536.812
       1  517.31  565.12
Encroach Node=7480.201
       1  521.64  567.96
Encroach Node=7018.827
       1  564.66  624.78
Encroach Node=5763.296
       1     430     510
Encroach Node=5042.04
       1  660.35     695
Encroach Node=4371.411
       1     553     644
Encroach Node=3784.971
       1     700  783.71
Encroach Node=3125.414
       1     520     720
Encroach Node=2615.371
       1  649.83   735.2
Encroach Node=1610.862
       1     674     829
Encroach Node=889.666
       1    5440    5620
Encroach Node=809.963
       1    5380    5520
Encroach Node=764.02
       1    5380    5520
Encroach Node=718.083
       1    5380    5520
Encroach Node=629.772
       1    5336    5480
Encroach Node=57.843
       1    4520 4608.89
BEGIN DESCRIPTION:
FEMA Effective June 2007 + LOMR 16-06-1829P
END DESCRIPTION:
Computation Interval=1HOUR
Output Interval=1HOUR
Run HTab= 1
Run UNet= 0
Run PostProcess= 0
UNET Theta= 1
UNET ZTol= 0.02
UNET ZSATol= 0.1
UNET MxIter= 20
UNET MaxInSteps= 20
UNET DtIC= 0
UNET DtMin= 0
UNET MaxCRTS= 20
UNET WFStab= 2
UNET SFStab= 1
UNET WFX= 1
UNET SFX= 1
UNET Convert EG Bridges=-1
UNET Use Existing IB Tables=-1
Instantaneous Interval=1HOUR
DSS File=dss
Write IC File= 0
IC Time=0
Write Velocity= 0
Write Detailed= 0

--- G103-80-031A.p01 (plan) ---

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Plan Title=FEMA Effective Multi-Profile 2016
Short Identifier=Eff+LOMR_MP
Geom File=g01
Flow File=f01
Encroach Param= 0 ,0,0, 2

--- G103-80-031A.f02 (steady flow) ---

Flow Title=Effective Floodway Feb 2017
Version=Version 3.0.1  Mar 2001
Number of Profiles= 2
Profile Names=1PCT_100yr, 1PCTFloodway_100yr
River Rch & RM=G103-80-031A,G10380031A_0001    ,8841.547
     144     144
River Rch & RM=G103-80-031A,G10380031A_0001    ,7664.522
     178     178
River Rch & RM=G103-80-031A,G10380031A_0001    ,7480.201
     185     185
River Rch & RM=G103-80-031A,G10380031A_0001    ,7018.827
     201     201
River Rch & RM=G103-80-031A,G10380031A_0001    ,5763.296
     253     253
River Rch & RM=G103-80-031A,G10380031A_0001    ,5042.04
     289     289
River Rch & RM=G103-80-031A,G10380031A_0001    ,4371.411
     327     327
River Rch & RM=G103-80-031A,G10380031A_0001    ,3784.971
     365     365
River Rch & RM=G103-80-031A,G10380031A_0001    ,3125.414
     412     412
River Rch & RM=G103-80-031A,G10380031A_0001    ,2615.371
     452     452
River Rch & RM=G103-80-031A,G10380031A_0001    ,1610.862
     544     544
River Rch & RM=G103-80-031A,G10380031A_0001    ,889.666
     642     642
River Rch & RM=G103-80-031A,G10380031A_0001    ,718.083
     652     652
River Rch & RM=G103-80-031A,G10380031A_0001    ,629.772
     725     725
Boundary for River Rch & Prof#=G103-80-031A,G10380031A_0001    , 1
Up Type= 0
Dn Type= 3
Dn Slope=.00142
DSS Import GetInterval= 0
DSS Import GetPeak= 0
DSS Import FillOption= 0

--- G103-80-031A.f01 (steady flow) ---

Flow Title=Effective Multi-Profile Feb 2017
Version=Version 3.0.1  Mar 2001
Number of Profiles= 4
Profile Names=10PCT_10yr, 2PCT_50yr, 1PCT_100yr, 0.2PCT_500yr
River Rch & RM=G103-80-031A,G10380031A_0001    ,8841.547
      12     105     144     328
River Rch & RM=G103-80-031A,G10380031A_0001    ,7664.522
      19     133     178     384
River Rch & RM=G103-80-031A,G10380031A_0001    ,7480.201
      20     138     185     394
River Rch & RM=G103-80-031A,G10380031A_0001    ,7018.827
      25     152     201     419
River Rch & RM=G103-80-031A,G10380031A_0001    ,5763.296
      41     196     253     496
River Rch & RM=G103-80-031A,G10380031A_0001    ,5042.04
      55     227     289     546
River Rch & RM=G103-80-031A,G10380031A_0001    ,4371.411
      72     260     327     598
River Rch & RM=G103-80-031A,G10380031A_0001    ,3784.971
      92     292     365     647
River Rch & RM=G103-80-031A,G10380031A_0001    ,3125.414
     120     334     412     707
River Rch & RM=G103-80-031A,G10380031A_0001    ,2615.371
     148     371     452     757
River Rch & RM=G103-80-031A,G10380031A_0001    ,1610.862
     223     454     544     866
River Rch & RM=G103-80-031A,G10380031A_0001    ,889.666
     321     544     642     977
River Rch & RM=G103-80-031A,G10380031A_0001    ,718.083
     333     554     652     988
River Rch & RM=G103-80-031A,G10380031A_0001    ,629.772
     421     622     725    1067
Boundary for River Rch & Prof#=G103-80-031A,G10380031A_0001    , 1
Up Type= 0
Dn Type= 3
Dn Slope=.00142
DSS Import GetInterval= 0
DSS Import GetPeak= 0
DSS Import FillOption= 0

--- G103-80-031A.g01 (geometry) ---

Geom Title=G103-80-031A
Program Version=4.10

River Reach=G103-80-031A    ,G10380031A_0001
Reach XY= 30
      3170364.86     13961207.32     3170480.299     13961386.47
     3170877.434     13961524.49      3171124.83     13961684.65
     3171394.361     13961679.44     3171898.268     13961800.53
     3172296.705     13962327.88     3172367.018     13962650.79
     3172714.674     13962991.94     3173239.413     13963049.23
     3173736.809     13962863.03     3174152.932      13963152.6
     3174385.247     13963588.29     3174558.424     13963762.77
     3174580.559     13964149.49      3174662.59     13964288.81
     3174650.872     13964361.73      3174537.59     13964435.95
     3174529.242     13964608.24     3174667.799     13964687.25
     3174795.403     13964613.03      3174874.83     13964632.56
     3174980.299     13964852.62      3175218.58     13964984.13
     3175671.705       13964906.     3175751.132     13964827.88
      3176162.59     13964877.36     3176885.247      13964343.5
     3177023.268     13964386.47     3177087.702     13964312.12

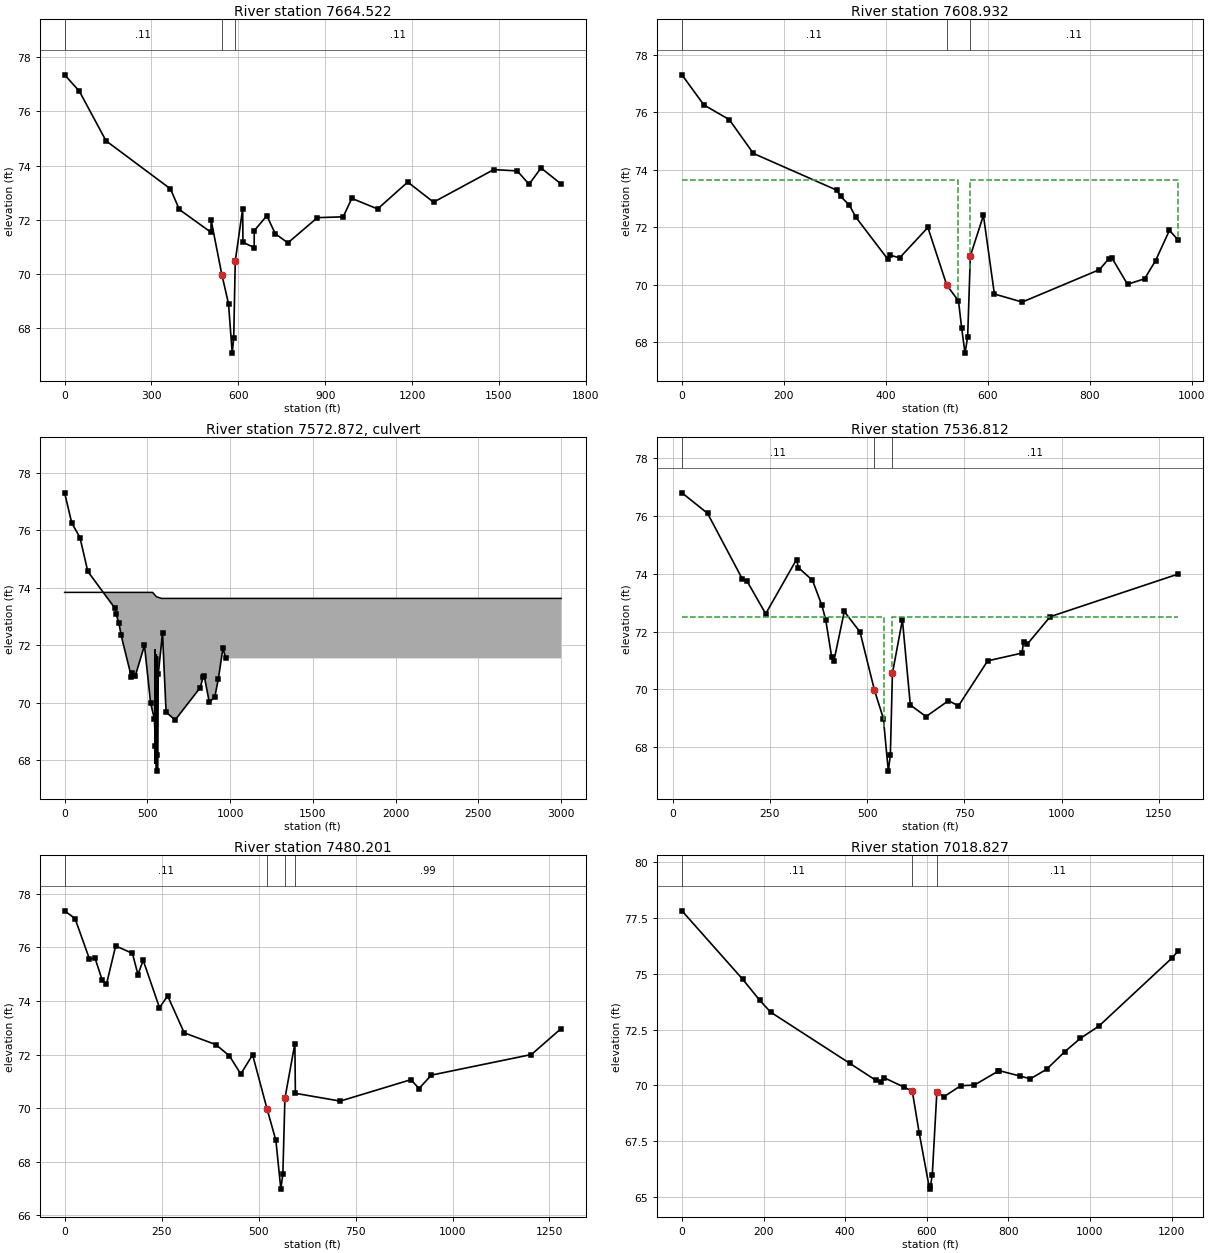
Type RM Length L Ch R = 1 ,7664.522,52.31,55.59,54.51
BEGIN DESCRIPTION:
414s1u:  XS 4/4
(Extended ROB)
Bank Station offset =      4421
XS modified to reflect revised orientation starting at Sta 654.86; based on 2001 LiDAR
END DESCRIPTION:
XS GIS Cut Line= 6
      3171519.74   13962104.0002   3171914.50018   13962068.0002
   3172113.34939   13961903.1217   3172127.99943   13961035.9964
   3172106.50374    13960886.001    3172087.4982   13960849.9971
#Sta/Elev= 30
       0   77.34   50.67   76.74  142.95   74.91  365.46   73.14  396.23   72.38
  505.45   71.54  505.97   71.99     543   69.98  566.04   68.91  578.79   67.09
  583.98   67.65  589.32   70.48  614.96   72.41  615.88   71.17  654.67   70.98
  654.86    71.6  698.41   72.15  727.45   71.49     771   71.15  872.97   72.08
  962.12   72.11  991.83   72.79 1080.98    72.4 1184.99   73.39 1274.14   72.65
 1482.15   73.85 1563.24    73.8 1603.99   73.31 1645.35   73.91 1714.67   73.32
#Mann= 3 ,-1 , 0
       0     .11       0     543     .06       0  589.32     .11       0
#Block Obstruct= 2 , 0
       0                  614.96       0   72.41
Bank Sta=543,589.32
XS Rating Curve= 0 ,0
Exp/Cntr=0.5,0.3

Type RM Length L Ch R = 1 ,7608.932,73.54,72.12,74.35
BEGIN DESCRIPTION:
Copy of 414s1u,  XS 3/4,  adjusted elevations by +0.52 ft between BS.
Block in right overbank due to watershed divide
Bank Station offset =      4445
END DESCRIPTION:
XS GIS Cut Line= 6
     3171558.185    13962134.206     3171962.277    13962081.443
     3172081.912    13962000.066     3172152.444    13961944.316
     3172410.198    13961735.065     3172410.198    13961735.065
#Sta/Elev= 29
       0   77.31   43.04   76.26    92.8   75.75  140.15   74.57   303.7   73.29
  311.47   73.07  328.36   72.77  341.52   72.34  403.64   70.89  407.52   71.03
  427.11   70.93  482.51   71.99  519.54   69.98  542.58   69.43  548.85   68.48
  555.33   67.61  560.52   68.17  565.86      71   591.5   72.41  613.01   69.67
  667.64   69.39   819.2   70.52  837.05   70.89  843.83   70.92  874.17   70.01
  907.64    70.2  929.14   70.83  956.45   71.89  974.11   71.54
#Mann= 3 ,-1 , 0
       0     .11       0  519.54     .06       0  565.86     .11       0
#XS Ineff= 2 , 0
       0     542   73.63     565       0   73.63
Permanent Ineff=
       F       F
#Block Obstruct= 2 , 0
       0                   591.5       0   72.41
Bank Sta=519.54,565.86
XS Rating Curve= 0 ,0
Exp/Cntr=0.5,0.3

Type RM Length L Ch R = 2 ,7572.872,,,
BEGIN DESCRIPTION:
Mills Branch Road 414s1
END DESCRIPTION:
Bridge Culvert--1,0,-1,-1, 0
Deck Dist Width WeirC Skew NumUp NumDn MinLoCord MaxHiCord MaxSubmerge Is_Ogee
11,50,2.6,0, 7, 7, 73.63, , 0.95, 0, 0,0,,
       0     480  531.76  554.45  585.19     595    3000
   73.84   73.84   73.84   73.69   73.63   73.63   73.63
       0       0       0       0       0       0       0
      24     480  531.76  554.45  585.19     595    3024
   73.84   73.84   73.84   73.69   73.63   73.63   73.63
       0       0       0       0       0       0       0
BR Coef=-1 , 0 , 0 ,, 0 ,,,0.8,-1,,0,
WSPro=,,,, 1 ,,,, 0 ,,,, 0 ,,,,-1 ,-1 ,-1 , 0 , 0 , 0 , 0 , 0
Culvert=1,4,,52.41,0.02,0.9,1,2,3,67.86,546.96,67.24,546.96,Culvert #1  , 0 ,9.8
Culvert Bottom n=0.02
Culvert=1,4,,52.39,0.02,0.9,1,2,3,67.68,555,67.17,555,Culvert #2  , 0 ,9.81
Culvert Bottom n=0.02
Culvert=1,4,,52.46,0.02,0.9,1,2,3,67.61,561.95,67.19,561.95,Culvert #3  , 0 ,9.77
Culvert Bottom n=0.02
BC Design=,, 0 ,, 0 ,,,,,,
BC HTab HWMax=77.31
BC Use User HTab Curves=0
BC User HTab FreeFlow(D)= 0

Type RM Length L Ch R = 1 ,7536.812,55.49,56.61,55.98
BEGIN DESCRIPTION:
Copy of 414s1u,  XS 2/4,  adjusted elevations by +0.08 ft between BS. (Extended ROB)
Bank Station offset =      4469
END DESCRIPTION:
XS GIS Cut Line= 6
     3171619.591    13962195.613     3172023.893    13962130.545
     3172121.531     13962060.13     3172168.779    13962027.787
     3172456.252    13961811.823 3172719.877813613961613.7741912
#Sta/Elev= 30
      24   76.81   89.79    76.1  179.05   73.83   191.8   73.74   239.3   72.62
  318.55    74.5  323.31   74.22  359.54   73.78   383.8   72.91  393.62   72.41
  409.09   71.11  414.71   70.99  441.38    72.7  481.77   71.99   518.8   69.98
  541.84   68.99  554.59   67.17  559.78   67.73  565.12   70.56  590.76   72.41
  611.14   69.46  651.59   69.06  709.25   69.61  734.89   69.43  809.98   70.99
  898.39   71.26  902.09   71.64  911.33   71.56   970.7   72.52 1300.43      74
#Mann= 3 ,-1 , 0
      24     .11       0   518.8     .06       0  565.12     .11       0
#XS Ineff= 2 , 0
      24     544    72.5     565      24    72.5
Permanent Ineff=
       F       F
#Block Obstruct= 2 , 0
       0                  590.76       0   72.41
Bank Sta=518.8,565.12
XS Rating Curve= 0 ,0
Exp/Cntr=0.5,0.3

Type RM Length L Ch R = 1 ,7480.201,421.85,461.37,493.92
BEGIN DESCRIPTION:
Copy of 414s1u,  XS 1/4,  adjusted elevations by -0.12 ft between BS.
(Extended ROB)
Assigned special ineffective to near ROB due to topographic divide.  The road is not overtopped and the 1% chance flow will not be effectively conveyed outside the main channel.
Bank Station offset =      4443
END DESCRIPTION:
XS GIS Cut Line= 6
     3171619.591    13962249.343     3172058.007    13962164.237
     3172139.245    13962117.162     3172160.206    13962102.142
 3172679.473792313961732.9294007 3172741.877403213961688.5588471
#Sta/Elev= 30
       0   77.37   26.94   77.08   63.75   75.58   78.67   75.59   96.49    74.8
  107.79   74.62   131.6   76.06  174.81   75.78   189.1   74.99   202.6   75.52
  244.57   73.75   265.7   74.19  308.35   72.81  389.89   72.37  424.87   71.95
   454.2   71.27  484.61   71.99  521.64   69.98  544.68   68.79  557.43   66.97
  562.62   67.53  567.96   70.36   593.6   72.41  594.92   70.55   710.6   70.26
  892.77   71.06  913.74   70.73  945.47   71.23 1203.43      72    1280   72.97
#Mann= 4 ,-1 , 0
       0     .11       0  521.64     .06       0  567.96     .11       0
   593.6     .99       0
Bank Sta=521.64,567.96
XS Rating Curve= 0 ,0
Exp/Cntr=0.3,0.1

Type RM Length L Ch R = 1 ,7018.827,1346.41,1255.53,1158.99
BEGIN DESCRIPTION:
414v6
Bank Station offset =      4391
END DESCRIPTION:
XS GIS Cut Line= 6
     3171737.597     13962634.45     3172285.624    13962504.109
     3172341.908    13962527.807     3172492.985    13962536.694
      3172691.46    13962504.109     3172863.273     13962338.22
#Sta/Elev= 28
       0   77.83  148.83   74.76  190.36   73.82  217.62   73.28  410.99   70.99
  475.49   70.22  486.78   70.15  495.41   70.34  543.08   69.93  564.66   69.73
  581.62   67.85  606.97   65.34  609.04   65.46  613.62   65.99  624.78   69.69
  642.27   69.49  683.24   69.98  716.57   70.01  775.72   70.64   777.1   70.66
  827.52   70.42  853.96   70.29  893.89   70.72  938.44   71.51  976.85   72.11
 1022.16   72.66 1200.99   75.71 1216.94   76.04
#Mann= 3 ,-1 , 0
       0     .11       0  564.66     .06       0  624.78     .11       0
Bank Sta=564.66,624.78
XS Rating Curve= 0 ,0
Exp/Cntr=0.3,0.1

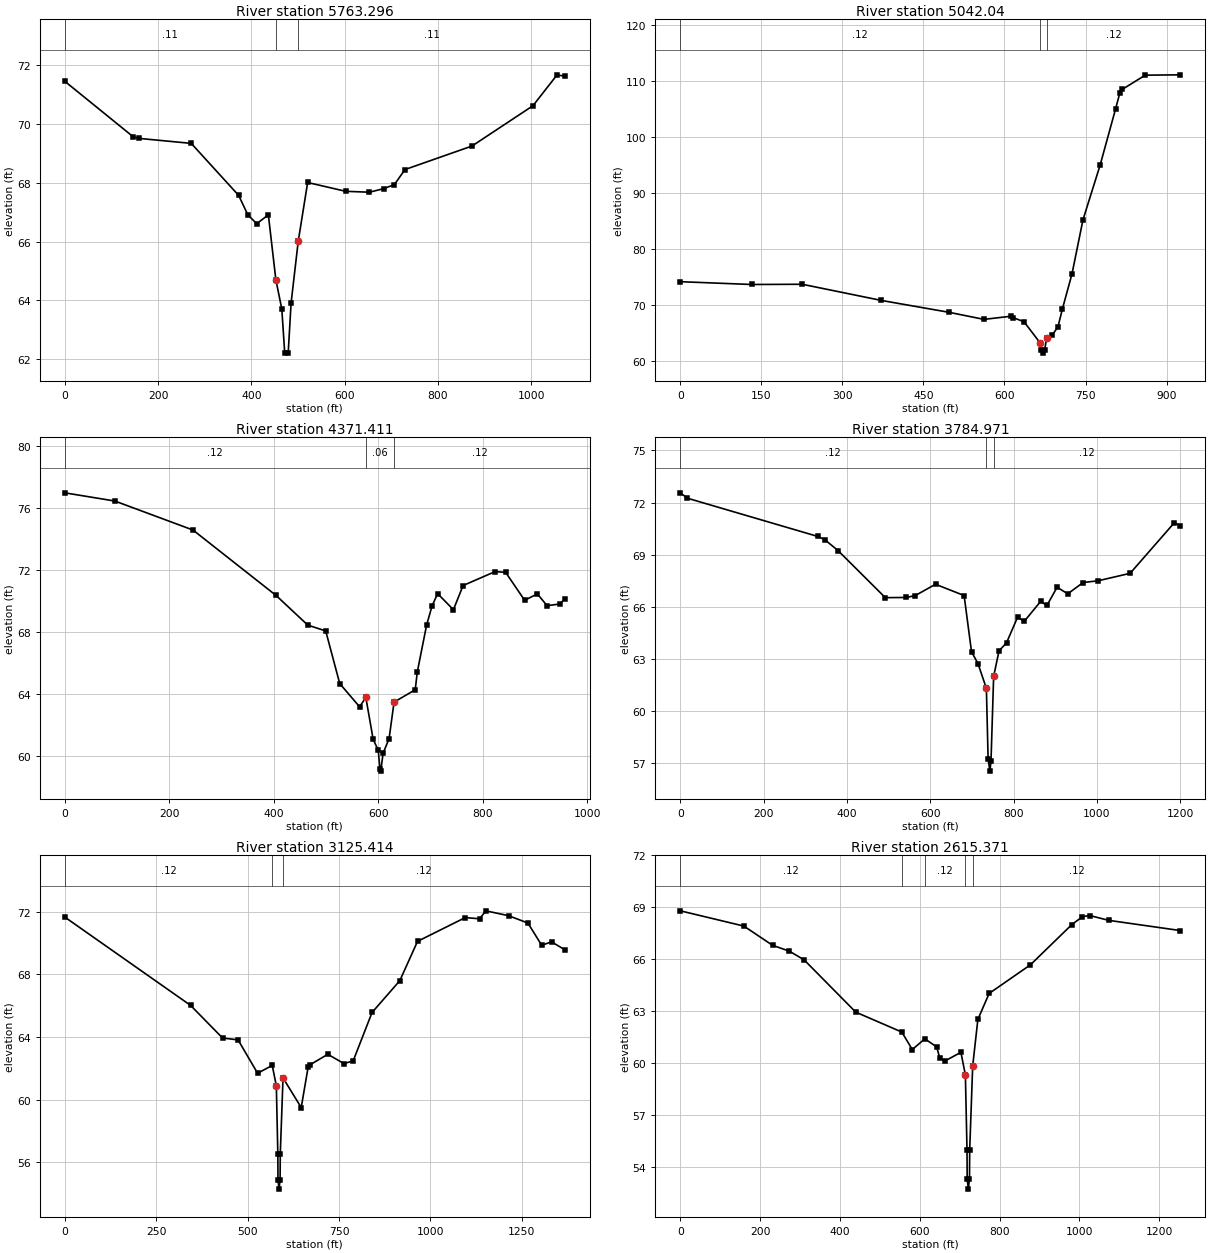
Type RM Length L Ch R = 1 ,5763.296,697.77,721.26,796.59
BEGIN DESCRIPTION:
414v2
Bank Station offset =      4528
END DESCRIPTION:
XS GIS Cut Line= 5
     3173350.749    13963480.526     3173349.338    13963074.019
     3173336.504    13963016.806     3173324.619    13962958.291
     3173192.608     13962427.14
#Sta/Elev= 24
       0   71.45   146.2   69.57  158.47   69.51  271.06   69.34  372.84   67.57
  392.45   66.91  411.45   66.61  436.45   66.91  452.45   64.71  465.25   63.71
  471.55   62.21  478.95   62.21  485.15   63.91  500.45   66.01  520.65   68.01
  602.45   67.71  653.15   67.68   683.5    67.8  706.69   67.94  729.35   68.45
   873.1   69.25 1003.77   70.62 1055.52   71.67 1072.16   71.62
#Mann= 3 , 0 , 0
       0     .11       0  452.45     .06       0  500.45     .11       0
Bank Sta=452.45,500.45
XS Rating Curve= 0 ,0
Exp/Cntr=0.3,0.1

Type RM Length L Ch R = 1 ,5042.04 ,639.65,670.63,687.71
BEGIN DESCRIPTION:
414v7
 The ROB high elevations are correct.  This is a large filled area.
Bank Station offset =      4329
END DESCRIPTION:
XS GIS Cut Line= 6
     3173570.239     13963575.42     3173783.503    13963344.385
     3173907.906    13963113.349     3173948.412    13963058.649
     3173962.745    13963026.307     3174130.056     13962846.77
#Sta/Elev= 25
       0   74.19  132.27   73.69  225.73   73.73  371.39   70.86  496.72   68.74
  562.13   67.47   611.3   68.02  615.28    67.8  636.06   67.06  665.56   63.33
  667.31   62.05  671.19   61.45  674.33   62.01  678.25   64.22   688.3   64.67
  698.99   66.13  707.21   69.31  725.09   75.63   745.3   85.22  777.14   95.01
  805.77  105.04  813.64  107.89  818.15  108.49  860.58  111.02  925.67  111.08
#Mann= 3 ,-1 , 0
       0     .12       0  665.56     .06       0  678.25     .12       0
Bank Sta=665.56,678.25
XS Rating Curve= 0 ,0
Exp/Cntr=0.3,0.1

Type RM Length L Ch R = 1 ,4371.411,529.82,586.44,605.45
BEGIN DESCRIPTION:
414v3
Bank Station offset =      4395
END DESCRIPTION:
XS GIS Cut Line= 5
     3173805.219    13963748.891      3174272.39    13963587.299
     3174365.675     13963535.77     3174453.007    13963489.862
     3174682.458    13963373.315
#Sta/Elev= 30
       0   76.98   95.86   76.45  245.32   74.58  404.29   70.36  464.86   68.45
   499.3   68.07  526.06   64.68  564.06   63.18  576.06   63.78  590.06   61.08
  599.76   60.38  603.06   59.18  604.56   59.03  609.06   60.18  620.56   61.13
  630.06   63.48  670.56   64.28  674.49   65.42  692.32   68.45  702.62   69.67
  713.42   70.48  743.62   69.44  762.12      71  823.43    71.9  843.59   71.85
  879.89   70.05  904.27   70.46  922.91    69.7  947.19   69.81  956.92   70.14
#Mann= 3 , 0 , 0
       0     .12       0  576.06     .06       0  630.06     .12       0
Bank Sta=576.06,630.06
XS Rating Curve= 0 ,0
Exp/Cntr=0.3,0.1

Type RM Length L Ch R = 1 ,3784.971,643.46,659.56,574.18
BEGIN DESCRIPTION:
414v8
Bank Station offset =      4257
END DESCRIPTION:
XS GIS Cut Line= 6
     3173878.443    13964149.718     3174280.898    13964053.556
     3174462.536    13964035.749     3174594.314    13964028.625
     3174768.829    13964049.995     3175064.438    13964053.556
#Sta/Elev= 30
       0   72.56   17.02   72.25  330.08   70.05  346.45   69.87  378.48   69.24
  492.04   66.53  542.83   66.54   563.9   66.65  612.56    67.3  681.23   66.65
  698.96   63.42  714.43   62.74  734.65   61.31  738.82   57.24  743.12   56.55
  745.74   57.12  752.08      62  765.01   63.47  782.98   63.93  809.43    65.4
  825.71   65.17  864.72   66.31  880.03   66.08  904.41   67.13  929.97   66.75
  966.83    67.4 1002.84    67.5 1079.75   67.93 1186.16   70.85 1200.41   70.66
#Mann= 3 ,-1 , 0
       0     .12       0  734.65     .06       0  752.08     .12       0
Bank Sta=734.65,752.08
XS Rating Curve= 0 ,0
Exp/Cntr=0.3,0.1

Type RM Length L Ch R = 1 ,3125.414,494.61,510.04,483.06
BEGIN DESCRIPTION:
XS added  on 11/08/02 due to sharp bend in stream.
copy of 414v4.  Added 1.57ft to surveyed section to create constant slope between XS 3910 and 25841.
Deleted two survey points on overbank that were copied to this location as the adjusted elevations do not reflect topography at this XS based on LIDAR and MrSID photos.  Points deleted:  Sta 609.82, el 64.09 and 638.12, el 65.59.
END DESCRIPTION:
XS GIS Cut Line= 3
      3173998.34    13964860.906     3174548.104    13964578.917
     3175144.158    13964124.045
#Sta/Elev= 30
       0   71.66  344.12   66.02  431.42   63.94  473.82   63.82  527.32   61.69
  567.32   62.19  578.52   60.89  582.62   56.54  583.02   54.89  585.92   54.29
  588.82   54.89  589.32   56.54  596.82   61.39  646.57    59.5  665.59   62.09
  669.93   62.22  719.35    62.9  763.16   62.31  788.49   62.47  840.33   65.57
  916.21    67.6  964.65   70.11 1095.33   71.63 1134.47   71.55 1151.39   72.06
 1213.53   71.75 1266.55   71.28 1304.29   69.86 1331.25   70.08 1367.65   69.57
#Mann= 3 ,-1 , 0
       0     .12       0  567.32     .06       0  596.82     .12       0
Bank Sta=578.52,596.82
XS Rating Curve= 0 ,0
Exp/Cntr=0.3,0.1

Type RM Length L Ch R = 1 ,2615.371,1032.69,1004.51,893.99
BEGIN DESCRIPTION:
414v4
Bank Station offset =      4278
END DESCRIPTION:
XS GIS Cut Line= 6
     3174451.958    13965219.875     3174784.358    13964815.916
     3174883.573    13964715.573     3174984.354    13964674.907
     3175095.849    13964494.042     3175227.213    13964260.401
#Sta/Elev= 28
       0   68.79  159.16   67.91  231.08    66.8   273.3   66.46   310.2   65.96
  439.74   62.94  555.18   61.79  581.38   60.78  612.91    61.4   642.6   60.93
  650.15    60.3  663.26   60.12  703.26   60.62  714.46   59.32  718.56   54.97
  718.96   53.32  721.86   52.72  724.76   53.32  725.26   54.97  732.76   59.82
  745.76   62.52  774.06   64.02  877.41   65.67  981.47      68 1007.82   68.45
 1025.98   68.52 1073.73   68.24 1253.44   67.65
#Mann= 5 ,-1 , 0
       0     .12       0  555.18     .99       0  612.91     .12       0
  714.46     .06       0  732.76     .12       0
Bank Sta=714.46,732.76
XS Rating Curve= 0 ,0
Exp/Cntr=0.3,0.1

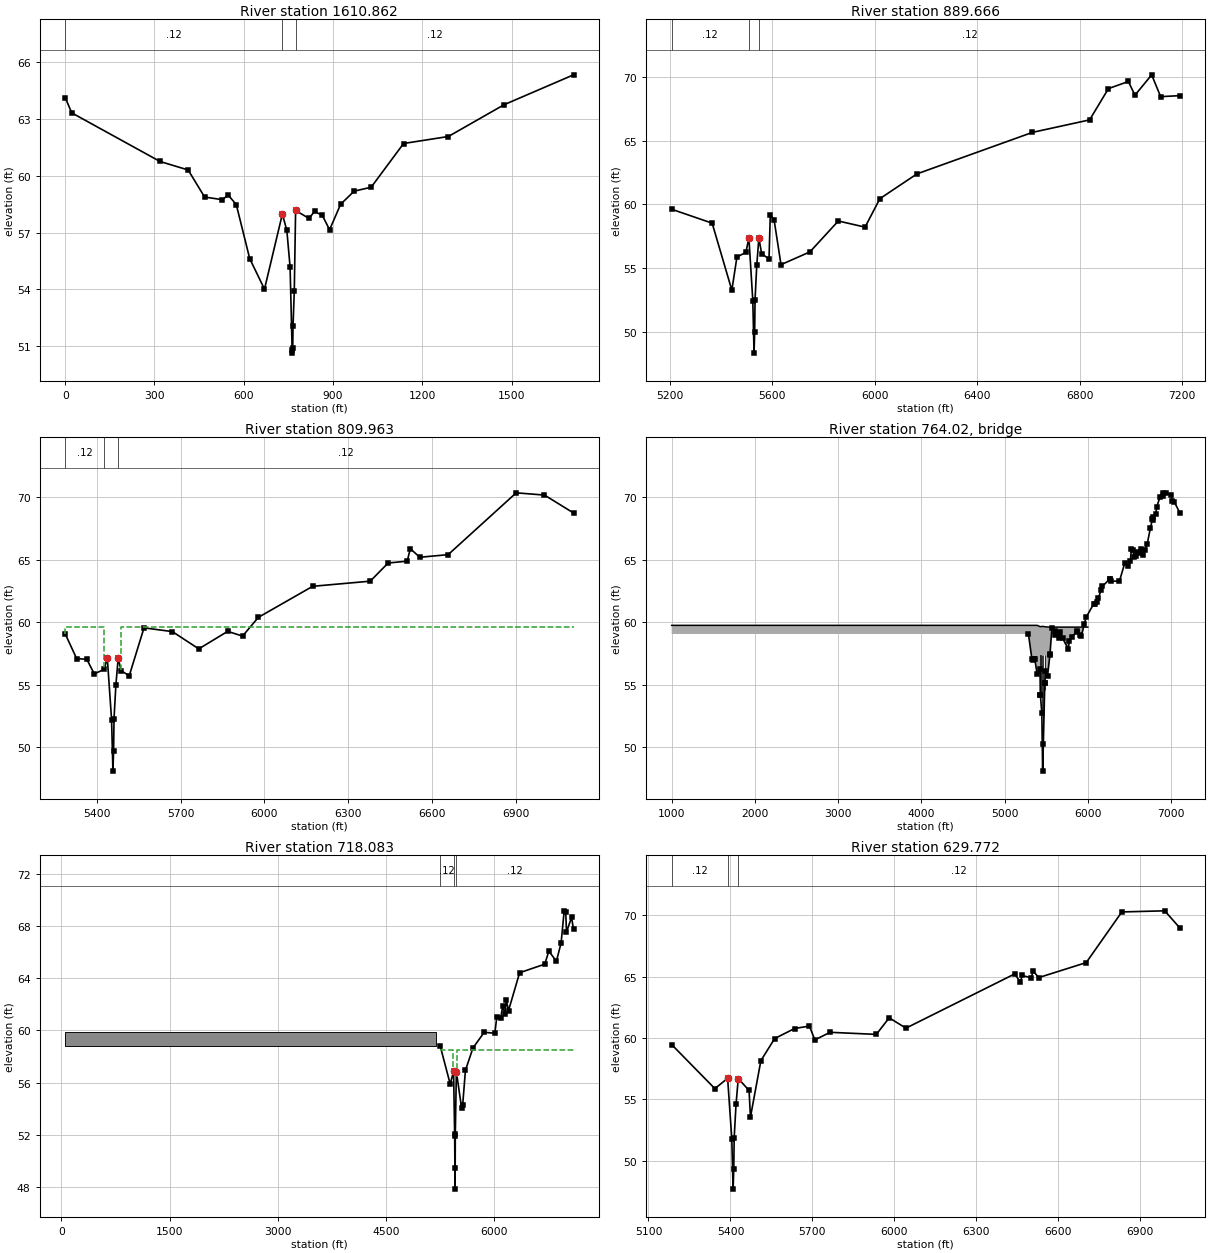
Type RM Length L Ch R = 1 ,1610.862,716.97,721.2,642.82
BEGIN DESCRIPTION:
414v9
Based on geometry at adjacent sections, removed 2 low points on near LOB.
Bank Station offset =      4236
END DESCRIPTION:
XS GIS Cut Line= 6
     3175826.608    13965556.528     3175815.923    13965221.743
     3175719.762    13964826.412     3175712.639     13964616.28
       3175669.9    13964359.849     3175548.808    13963879.041
#Sta/Elev= 30
       0   64.14   21.87   63.33   318.6   60.76  413.15   60.31  468.44   58.88
  528.38   58.74  547.44   58.99  574.86   58.48  619.89   55.63  669.62   54.01
  729.66   57.98  744.73   57.12  755.65   55.18  762.52   50.82  763.51   50.63
  764.61   50.88  765.48   52.04  769.75   53.93  774.21   58.17   819.2   57.75
  837.84   58.12  864.03   57.91   888.4   57.15  925.55    58.5  970.86   59.19
 1028.11    59.4 1136.99   61.71 1287.44   62.08 1474.74   63.76  1708.1   65.34
#Mann= 3 ,-1 , 0
       0     .12       0  729.66     .06       0  774.21     .12       0
Bank Sta=729.66,774.21
XS Rating Curve= 0 ,0
Exp/Cntr=0.3,0.1

Type RM Length L Ch R = 1 ,889.666 ,76.93,79.7,79.02
BEGIN DESCRIPTION:
copy of 414s2d, XS 4/4, adjusted elevations by +0.53 ft between CB.
Bank Station offset =      -529
END DESCRIPTION:
XS GIS Cut Line= 6
 3176537.9744904 13964990.408281     3176515.127    13964960.298
     3176422.953    13964806.435     3176357.715    13964704.197
     3176017.321    13964192.382     3175426.784    13963346.981
#Sta/Elev= 30
  5207.5   59.62 5365.53   58.53 5442.42   53.28 5462.27   55.88 5497.29   56.24
 5508.95   57.38  5524.2   52.46 5529.02   48.35 5531.46   49.99 5532.99   52.55
 5539.69   55.25 5547.87   57.36 5558.87   56.13 5587.49   55.73  5592.5    59.2
 5607.21    58.8  5634.3   55.28 5747.18   56.28 5858.03    58.7 5962.35   58.22
 6020.32   60.45 6164.96   62.39 6615.55   65.64 6839.03   66.62 6912.38   69.07
 6990.44   69.63 7015.87   68.55 7081.26   70.15 7116.27   68.44 7191.84   68.52
#Mann= 3 ,-1 , 0
  5207.5     .12       0 5508.95     .06       0 5547.87     .12       0
#Block Obstruct= 1 ,-1
       0 5207.51   59.62
Bank Sta=5508.95,5547.87
XS Rating Curve= 0 ,0
Exp/Cntr=0.5,0.3

Type RM Length L Ch R = 1 ,809.963 ,90.54,91.88,96.75
BEGIN DESCRIPTION:
copy of 414s2d, XS 3/4, adjusted elevations by +0.29 ft between CB.
Bank Station offset =      -457
Cross Section's left overbank truncated to remove White Oak Creek Watershed
END DESCRIPTION:
XS GIS Cut Line= 6
 3176522.797542413964825.0224304     3176451.953    13964706.435
     3176411.204    13964643.379     3176386.715    13964604.197
     3176046.321    13964092.382     3175503.542    13963316.278
#Sta/Elev= 30
 5286.52   59.08 5327.36   57.11 5364.11   57.04  5390.7   55.88 5425.72   56.24
 5437.38   57.14 5452.63   52.22 5457.45   48.11 5459.89   49.75 5461.42   52.31
 5468.12   55.01  5476.3   57.12  5487.3   56.13 5515.92   55.73 5568.81   59.56
 5670.49   59.26 5765.02   57.88 5868.73   59.28 5921.87    58.9 5978.65    60.4
 6173.19   62.88  6379.4   63.29 6443.37   64.74 6511.81   64.89 6522.99   65.89
 6556.71    65.2 6658.48   65.41 6902.28   70.35 7003.63   70.17 7107.69   68.74
#Mann= 3 ,-1 , 0
 5286.52     .12       0 5425.72    .045       0  5476.3     .12       0
#XS Ineff= 2 , 0
       0    5425   59.63    5487       0   59.63
Permanent Ineff=
       F       F
#Block Obstruct= 1 ,-1
       0 5286.52   59.08
Bank Sta=5437.38,5476.3
XS Rating Curve= 0 ,0
Exp/Cntr=0.5,0.3

Type RM Length L Ch R = 3 ,764.02  ,,,
BEGIN DESCRIPTION:
Hueni Road 414s2
END DESCRIPTION:
Bridge Culvert--1,0,0,-1, 0
Deck Dist Width WeirC Skew NumUp NumDn MinLoCord MaxHiCord MaxSubmerge Is_Ogee
32.14,27.12,2.6,0, 10, 10, 59.63, , 0.95, 0, 0,0,,
    1000    5377 5392.53 5429.46 5429.46    5457 5483.62 5483.62 5531.12    6000
   59.77   59.77   59.77   59.66   59.66   59.69   59.66   59.66   59.63   59.63
       0       0       0       0   57.38   57.38   57.38       0       0       0
    1054    5378 5393.53 5430.46 5430.46    5458 5484.62 5484.62 5532.12    6054
   59.77   59.77   59.77   59.66   59.66   59.69   59.66   59.66   59.63   59.63
       0       0       0       0   57.38   57.38   57.38       0       0       0
Pier Skew, UpSta & Num, DnSta & Num=  ,5432, 2 ,5433, 2 , 0 , 0 , 0 ,0,
       1       1
   47.82   57.38
       1       1
   47.82   57.38
Pier Skew, UpSta & Num, DnSta & Num=  ,5447.41, 2 ,5448.41, 2 , 0 , 0 , 0 ,0,
       1       1
   47.82   57.38
       1       1
   47.82   57.38
Pier Skew, UpSta & Num, DnSta & Num=  ,5465.62, 2 ,5466.62, 2 , 0 , 0 , 0 ,0,
       1       1
   47.82   57.38
       1       1
   47.82   57.38
Pier Skew, UpSta & Num, DnSta & Num=  ,5481, 2 ,5482, 2 , 0 , 0 , 0 ,0,
       1       1
   47.82   57.38
       1       1
   47.82   57.38
BR Coef=-1 , 0 , 0 ,, 0 ,,,0.8,0,,0,
WSPro=,,,, 1 ,,,, 0 ,,,, 0 ,,,,-1 ,-1 ,-1 , 0 , 0 , 0 , 0 , 0
BR U #Sta/Elev= 72
 5286.52   59.08 5327.36   57.11 5338.02   57.03 5354.42   57.04 5355.62   57.04
 5364.11   57.04  5390.7   55.88 5425.72   56.24  5429.5   54.22    5430   54.22
 5447.41   52.76 5457.45   48.11 5465.62   50.26    5483   55.15  5483.5   55.15
  5487.3   56.13 5515.92   55.73 5544.49   57.38 5545.94   57.51 5568.81   59.56
 5605.41   59.28  5611.3   58.99 5625.38   59.15 5658.74   58.79 5670.49   59.26
    5696   58.75 5765.02   57.88 5778.66   58.55 5805.78   58.83 5868.73   59.28
 5873.75   59.21 5909.42   59.01 5921.87    58.9  5958.8   59.89 5978.65    60.4
  6070.3   61.48 6092.21   61.45 6105.61   61.66 6128.44   61.98 6160.62   62.62
 6173.19   62.88 6266.73   63.49 6268.94   63.51 6278.46   63.32  6379.4   63.29
 6443.37   64.74 6486.38   64.53 6511.81   64.89 6522.99   65.89 6540.19   65.82
 6556.71    65.2 6576.55   65.29 6596.21   65.64 6612.78   65.56 6637.78   65.86
 6658.48   65.41 6681.23   65.77  6714.1   66.29 6751.03   67.52 6776.88   68.27
 6779.25   68.23 6782.31    68.4 6815.86   68.67 6829.07   69.27 6869.64   70.07
 6902.28   70.35 6907.38   70.11 6945.02   70.37 7003.63   70.17 7012.74   69.71
 7037.47   69.67 7107.69   68.74
BR U #Mann= 3
 5286.52     .12  5429.5     .04    5483     .12
BR U Banks=5429.5,5483.5
BR D #Sta/Elev= 124
 5221.81   59.84 5252.94   58.79 5268.45    58.5 5280.47   58.28 5293.21   58.37
 5333.18   57.34 5364.91   56.96 5390.89   55.88 5425.91   56.24  5430.5   55.72
    5431   55.72 5448.41   52.93 5457.64   47.82 5466.62   52.12    5484   55.01
  5484.5   55.01 5487.49   56.13 5516.11   55.73 5533.15   54.09 5543.57   54.04
 5548.14   54.07 5549.09    54.1    5564   54.29 5591.07   56.05 5601.91   56.93
 5628.46   57.32 5628.93   57.42 5632.74   57.39 5680.14   57.79 5682.97   57.73
 5700.04   58.32 5706.58   58.65 5750.75   58.98 5758.71   58.97 5801.09   58.77
 5819.91   59.09 5824.56   59.09 5838.36   58.85 5844.11   58.92 5847.02   59.06
 5862.12   59.85 5874.12    59.2  5876.7   59.25 5881.84   59.26 5912.43   59.32
  5920.4   59.47 5961.76   59.67 5974.37   59.77 5999.39   59.76 6007.57   59.93
 6009.63   59.78 6018.39    60.1 6036.74   61.02 6054.37   60.93 6090.94   60.92
 6096.24   61.16 6118.05   61.85 6124.15   61.52 6145.15   61.22 6150.27   61.24
 6152.82   61.38 6168.28   62.32 6199.36   61.52  6204.3   61.62 6210.17   61.78
  6225.6   62.29 6234.62   62.21 6249.83   62.61 6276.95   62.87 6288.35   62.76
 6307.58   63.25 6320.59   63.64 6328.31   63.69    6352   64.28 6353.17   64.42
 6353.98    64.3 6374.32   64.19 6379.66   64.26 6395.82   64.06 6423.08   64.54
 6428.06   64.64 6480.47   65.04 6481.79   65.04 6484.59    65.1 6514.03   64.84
 6518.34   64.83 6535.52   65.17 6536.82   65.21 6544.82   65.32 6554.02   65.21
 6558.09   65.31 6559.38   65.21 6568.66   65.44 6589.25   65.39  6607.3   65.28
 6610.74   65.26 6629.23   65.15 6642.98   65.42 6662.09   65.32 6684.68   65.24
 6701.65   65.08 6732.34   65.58 6750.45   65.88 6758.61   66.08 6777.41   66.03
 6812.88   65.71 6814.05   65.68 6816.14   65.71 6836.42   65.86 6862.92    65.3
 6867.49   65.39  6869.5   65.45 6918.84   66.73 6922.39   66.74 6928.38   66.71
    6971   69.17 6992.87   69.05 7002.67   67.54 7017.35   67.39 7021.54    67.5
 7072.75   68.65 7072.84   68.66 7072.98   68.65 7100.56   67.76
BR D #Mann= 3
 5221.81     .12  5430.5     .04  5484.5     .12
BR D Banks=5430.5,5484.5
BC Design=,, 0 ,, 0 ,,4,4970,4979,17,1
BC HTab HWMax=70.37
BC Use User HTab Curves=0
BC User HTab FreeFlow(D)= 0

Type RM Length L Ch R = 1 ,718.083 ,88.71,88.31,88.24
BEGIN DESCRIPTION:
414s2d:  XS 2/4
Bank Station offset =      -404
Cross Section's left overbank truncated to remove White Oak Creek Watershed
END DESCRIPTION:
XS GIS Cut Line= 6
 3176623.320705913964795.5858014     3176555.649    13964706.382
     3176466.904    13964546.149     3176412.371    13964481.476
     3176092.802     13964000.54     3175572.624    13963277.899
#Sta/Elev= 30
 5252.94   58.79 5390.89   55.88 5437.57   56.85 5452.82   51.93 5457.64   47.82
 5460.08   49.46 5461.61   52.02 5476.49   56.83 5548.14   54.07    5564   54.29
 5601.91   56.93 5706.58   58.65 5862.12   59.85 6009.63   59.78 6036.74   61.02
 6090.94   60.92 6118.05   61.85 6150.27   61.24 6168.28   62.32 6199.36   61.52
 6353.17   64.42 6701.65   65.08 6758.61   66.08 6862.92    65.3 6928.38   66.71
    6971   69.17 6992.87   69.05 7002.67   67.54 7072.84   68.66 7100.56   67.76
#Mann= 3 ,-1 , 0
 5252.94     .12       0 5437.57    .045       0 5476.49     .12       0
#XS Ineff= 2 , 0
       0    5425    58.5    5487       0    58.5
Permanent Ineff=
       F       F
#Block Obstruct= 1 ,-1
      54 5198.12   59.86
Bank Sta=5437.57,5476.49
XS Rating Curve= 0 ,0
Exp/Cntr=0.5,0.3

Type RM Length L Ch R = 1 ,629.772 ,576.61,571.93,385.92
BEGIN DESCRIPTION:
copy of 414s2d, XS 1/4, adjusted elevations by -0.13 ft between BS.
Bank Station offset =      -410
Cross Section's left overbank truncated to remove White Oak Creek Watershed
END DESCRIPTION:
XS GIS Cut Line= 6
 3176709.794204813964766.7554372     3176633.649    13964666.382
     3176544.904    13964506.149     3176490.371    13964441.476
     3176170.802     13963960.54     3175672.409    13963224.169
#Sta/Elev= 30
 5184.92   59.47 5343.01   55.88 5389.69   56.72 5404.94    51.8 5409.76   47.69
  5412.2   49.33 5413.73   51.89 5420.43   54.59 5428.61    56.7 5468.23   55.73
 5473.25   53.56  5511.4   58.16  5561.8   59.96 5634.74   60.78 5689.18   60.98
 5708.83   59.85 5764.63   60.47 5933.95    60.3 5980.98   61.65 6042.37   60.81
 6440.58   65.23 6461.56   64.54 6467.36    65.1 6500.45   64.91 6508.03   65.46
 6528.33   64.93 6702.11   66.15 6832.47   70.28 6989.49   70.37 7045.35   68.96
#Mann= 3 ,-1 , 0
 5184.92     .12       0 5389.69     .06       0 5428.61     .12       0
#Block Obstruct= 1 ,-1
       0 5184.92   59.47
Bank Sta=5389.69,5428.61
XS Rating Curve= 0 ,0
Exp/Cntr=0.3,0.1

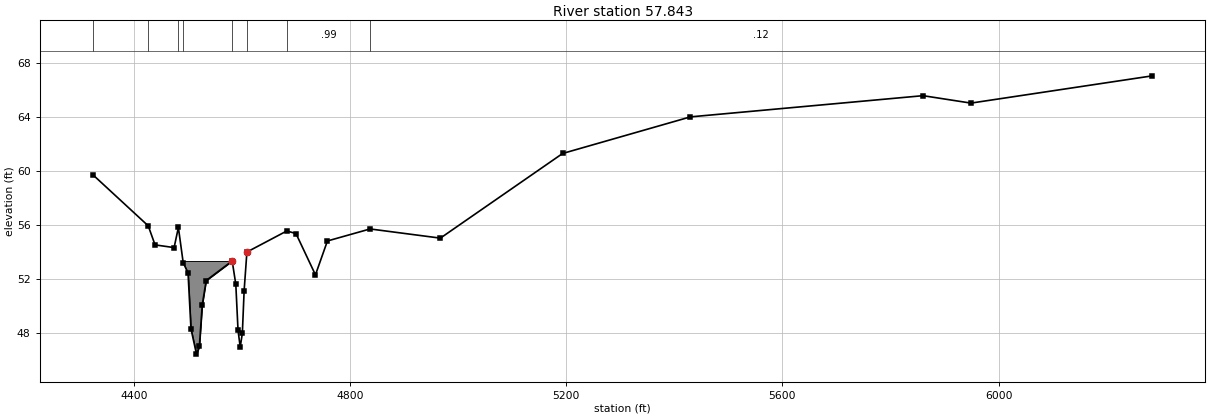
Type RM Length L Ch R = 1 ,57.843  ,32.43,57.84,256.73
BEGIN DESCRIPTION:
414v5
The main portion of the White Oak Creek channel is blocked to allow for flows from White Oak.  Mannings "n" set to 0.01 over the blocked area due to flow over water.
Bank Station offset =       403
END DESCRIPTION:
XS GIS Cut Line= 6
 3177301.629699413964439.0001849     3177117.689    13964376.791
      3176995.38     13964339.02     3176912.158    13964316.591
     3176764.318    13964245.627     3175848.953    13963201.141
#Sta/Elev= 30
 4323.64    59.7 4426.29   55.91  4438.9    54.5 4474.16    54.3 4482.08   55.79
 4490.99   53.18 4499.95   52.42 4505.38   48.28 4515.61   46.41 4520.92   46.98
  4526.2   50.04 4533.52   51.86 4581.65   53.31 4588.36   51.58 4592.46   48.18
 4596.53   46.93 4600.48   47.96 4603.77   51.11 4608.89   53.97  4682.7   55.53
 4699.72   55.34 4735.77   52.28 4757.91   54.79  4836.9   55.68 4966.96      55
 5193.24   61.27 5429.74   63.98 5860.31   65.55 5948.92      65 6284.85   67.02
#Mann= 8 ,-1 , 0
 4323.64     .12       0 4426.29     .99       0 4482.08     .12       0
 4490.99     .01       0 4581.65     .06       0 4608.89     .12       0
  4682.7     .99       0  4836.9     .12       0
#Block Obstruct= 1 ,-1
    4480 4581.65   53.31
Bank Sta=4581.65,4608.89
XS Rating Curve= 0 ,0
Exp/Cntr=0.3,0.1

Chan Stop Cuts=-1
Use User Specified Reach Order=0
Composite Channel Slope=5